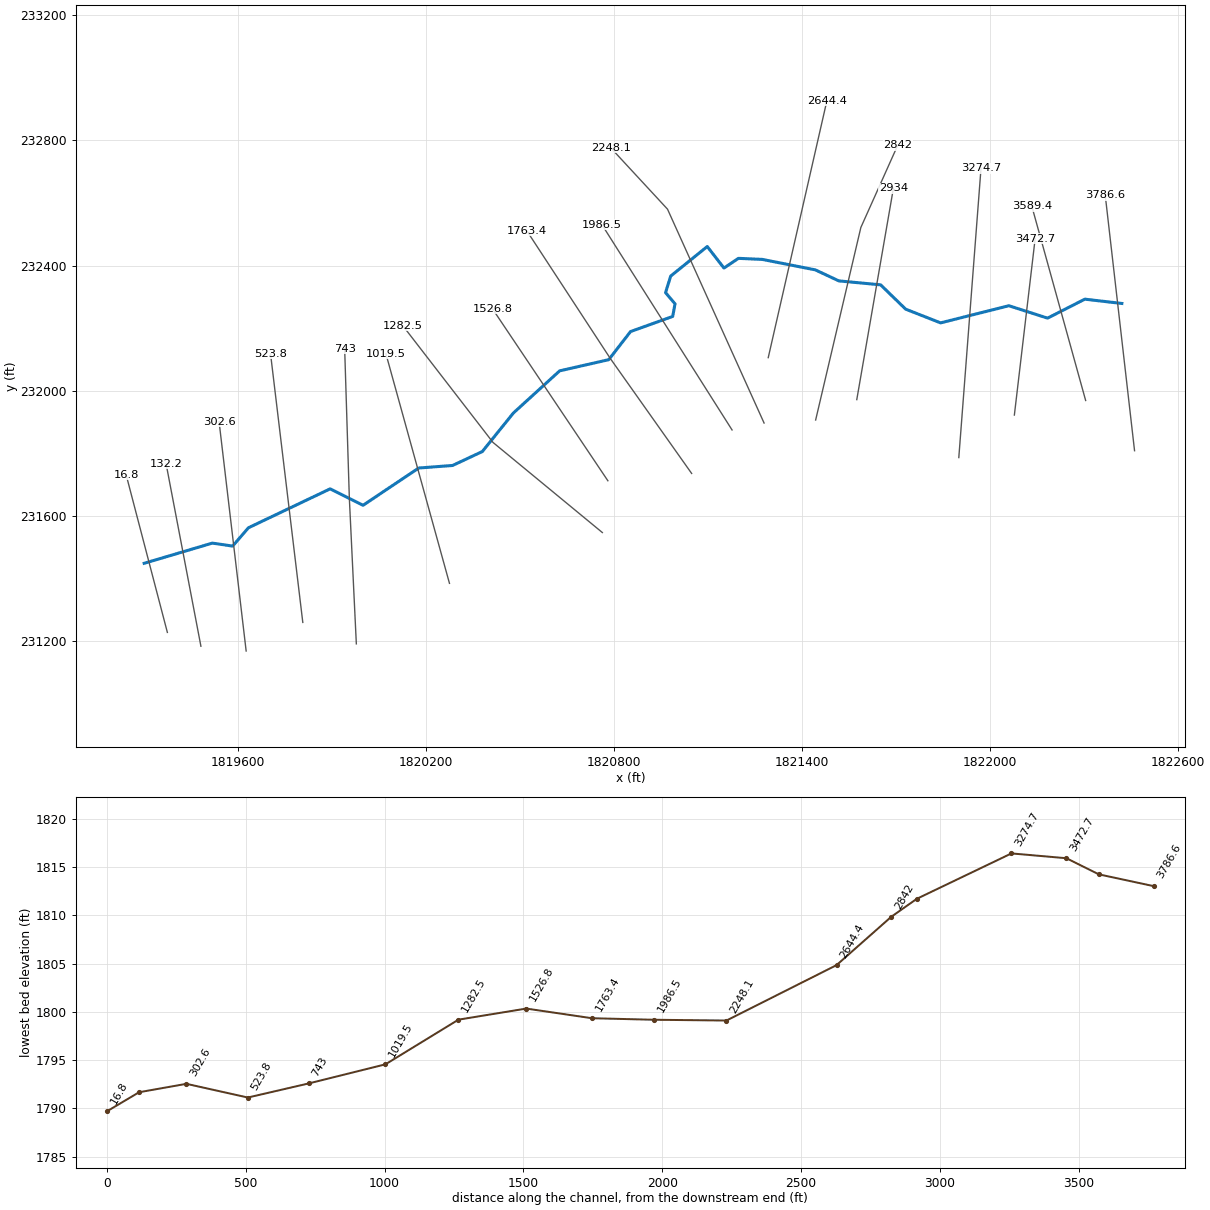
--- RckcastlCr.prj (project) ---

Proj Title=RckcastlCr
Current Plan=p01
Default Exp/Contr=0,0
English Units
Geom File=g01
Flow File=f01
Plan File=p01
BEGIN DESCRIPTION:
END DESCRIPTION:
DSS Export Rating Curves= 0
DSS Export Rating Curve Sorted= 0
DSS Export Volume Flow Curves= 0
DXF OffsetX= 0
DXF OffsetY= 0
DXF ScaleX= 0
DXF ScaleY= 0

--- RckcastlCr.p01 (plan) ---

Plan Title=Floodplain
Program Version=4.00
Geom File=g01
Flow File=f01
K Sum by GR=0
Std Step Tol=0.01
Critical Tol=0.01
Num of Std Step Trials=20
Max Error Tol=0.3
Flow Tol Ratio=0.001
Split Flow NTrial=30
Split Flow Tol=0.02
Split Flow Ratio=0.02
Log Output Level=0
Friction Slope Method=1
Unsteady Friction Slope Method=2
Unsteady Bridges Friction Slope Method=1
Global Log Level=0
CheckData=False
Run HTab=0
Run UNet=0
Run PostProcess=0
UNET Theta=0
UNET Theta Warmup=0
UNET ZTol=0
UNET ZSATol=0
UNET MxIter=0
UNET MaxInSteps=0
UNET DtIC=0
UNET DtMin=0
UNET MaxCRTS=0
UNET WFStab=0
UNET SFStab=0
UNET WFX=0
UNET SFX=0
UNET DSS MLevel=0
UNET DZMax Abort=0
UNET Convert EG Bridges=0
UNET Use Existing IB Tables=0
UNET Froude Limit=0
UNET Froude Power=0
Write IC File=0
Echo Input=False
Echo Output=False
Write Detailed=0

--- RckcastlCr.f01 (steady flow) ---

Flow Title=NFF Regression Equation
Program Version=4.00
Number of Profiles=1
Profile Names=P100yr
River Rch & RM=RckcastlCr,Main      ,3786.6
1580.097
River Rch & RM=RckcastlCr,Main      ,3589.4
529.1936
River Rch & RM=RckcastlCr,Main      ,3472.7
605.2120
River Rch & RM=RckcastlCr,Main      ,2248.1
634.4496
River Rch & RM=RckcastlCr,Main      ,2248.1
868.5105
River Rch & RM=RckcastlCr,Main      ,132.2
899.9617
Boundary for River Rch & Prof#=RckcastlCr,Main      ,1
Up Type=0
Dn Type=3
Dn Slope=0.003977

--- RckcastlCr.g01 (geometry) ---

Geom Title=USGS 10m DEM
Program Version=4.00

River Reach=RckcastlCr      ,Main
Reach XY= 30
     1822420.249      232279.031     1822302.144      232292.738
     1822183.282      232232.179     1822059.843      232271.823
     1821842.129      232217.065     1821730.614      232260.914
     1821650.782      232338.498     1821517.432      232351.112
     1821442.648      232386.252     1821273.245      232419.699
      1821197.19       232423.05     1821151.162       232392.01
     1821097.882      232460.813     1820981.252      232366.418
      1820964.89      232313.557     1820995.096      232277.897
     1820987.635      232237.585     1820853.295      232189.377
     1820783.653      232099.597     1820627.168      232063.937
     1820479.493      231929.267     1820380.484      231806.345
      1820285.67      231761.875     1820177.622       231753.74
     1820000.122      231634.806     1819895.088      231687.198
     1819634.559      231563.017     1819584.075      231504.572
     1819519.497      231514.073     1819301.978      231449.587

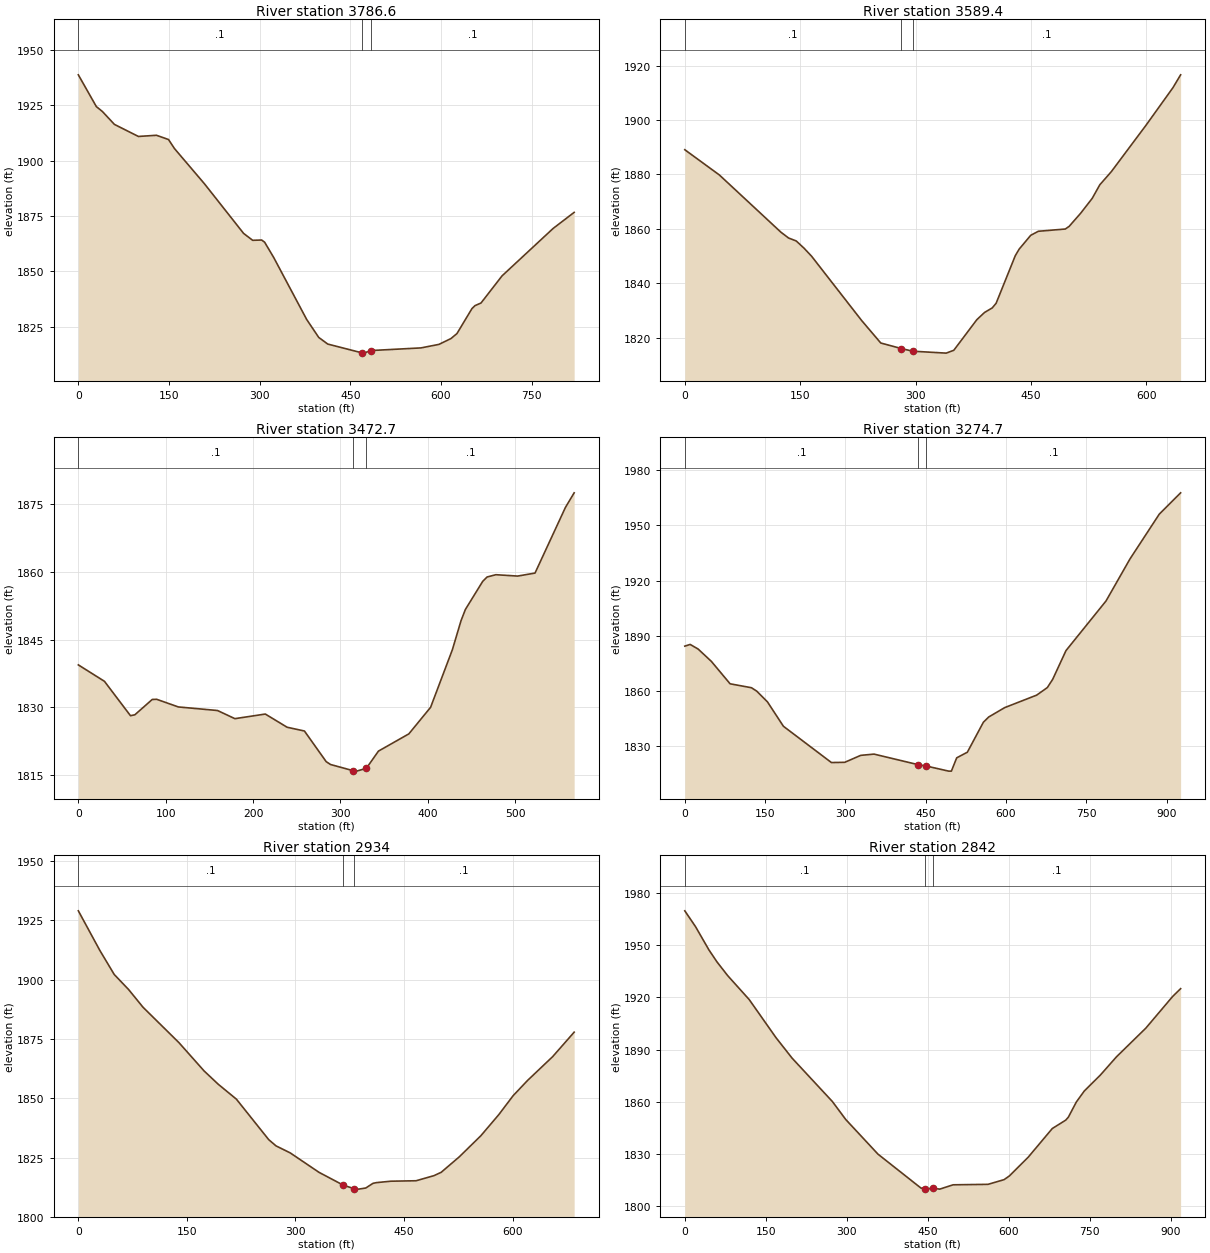
Type RM Length L Ch R = 1 ,3786.6  ,194,197.2,200.5
XS GIS Cut Line= 2
     1822460.709      231808.993     1822367.267      232623.987
#Sta/Elev= 30
       0 1938.85    29.8 1924.49    39.8 1922.28    59.7 1916.44    99.4 1910.99
   129.3 1911.52   149.2  1909.6   159.1  1905.5   208.8 1889.55   273.4 1867.17
   288.4 1864.04   303.3 1864.17   308.2 1863.19   323.2 1856.29   377.8 1828.25
   397.7 1820.15   412.6 1817.14   468.9 1813.19   472.3 1813.04   483.9  1814.2
   566.8  1815.4   596.6 1816.99   616.5 1819.63   626.4 1821.88   651.3  1833.2
   656.3 1834.52   666.2  1835.7     701 1847.96   785.5  1869.4   820.3 1876.67
#Mann= 3 , 0 , 0
       0      .1       0   468.9    .045       0   483.9      .1       0
Bank Sta=468.9,483.9
XS Rating Curve= 0 ,0
Exp/Cntr=0.3,0.1

Type RM Length L Ch R = 1 ,3589.4  ,125.5,116.7,108.7
XS GIS Cut Line= 2
     1822304.755      231969.293     1822132.842      232590.285
#Sta/Elev= 30
       0 1889.08      45 1879.78   124.9 1858.75   134.9  1856.6   144.8 1855.52
   154.8 1852.91   164.8  1849.9   229.8 1826.27   254.7 1817.98   281.2 1815.96
   296.2 1814.97   339.7 1814.26   349.6  1815.3   379.6 1826.58   389.6 1829.22
   399.6  1830.9   404.6 1832.59   429.6 1850.15   434.6 1852.53   449.6  1857.6
   459.5 1859.08   494.5 1859.91   499.5 1860.88   514.5 1865.72   529.5 1871.19
   539.4 1876.19   554.4 1881.03   599.4 1898.08   634.4 1911.89   644.4 1916.63
#Mann= 3 , 0 , 0
       0      .1       0   281.2    .045       0   296.2      .1       0
Bank Sta=281.2,296.2
XS Rating Curve= 0 ,0
Exp/Cntr=0.3,0.1

Type RM Length L Ch R = 1 ,3472.7  ,197.7,198,197.7
XS GIS Cut Line= 2
     1822077.393      231922.814     1822143.738      232486.383
#Sta/Elev= 30
       0  1839.4    29.9 1835.77    59.7 1828.17    64.7 1828.38    84.6 1831.76
    89.6  1831.8   114.5 1830.11   159.3 1829.32   179.2 1827.52     214 1828.54
   238.9 1825.63   258.8 1824.79   283.7 1818.02   288.7 1817.39   314.7 1816.02
   318.6 1815.93   329.7 1816.56   343.5 1820.35   378.3 1824.16   403.2 1830.03
   428.1 1842.74     438 1849.15     443 1851.64   462.9 1857.87   467.9 1858.82
   477.9 1859.32   502.8 1859.02   522.7 1859.68   557.5 1874.18   567.5 1877.41
#Mann= 3 , 0 , 0
       0      .1       0   314.7    .045       0   329.7      .1       0
Bank Sta=314.7,329.7
XS Rating Curve= 0 ,0
Exp/Cntr=0.3,0.1

Type RM Length L Ch R = 1 ,3274.7  ,342.2,340.7,339.2
XS GIS Cut Line= 2
     1821900.202      231787.089     1821971.044      232710.554
#Sta/Elev= 30
       0 1884.36      10  1885.3    24.9 1882.79    49.8 1876.03    84.6  1863.9
   124.5 1861.76   134.4 1859.91   154.4 1854.08   184.2 1840.82   273.9 1821.09
   298.8 1821.22   328.6    1825   353.5 1825.68   436.2 1819.92   451.2 1819.19
     493 1816.43     498 1816.43   507.9 1823.65   527.8 1826.71   557.7 1842.98
   567.7 1845.85   597.5 1850.94   657.3 1857.74   677.2 1861.84   687.2 1866.32
   712.1 1881.96   786.8  1908.9   831.6 1931.76   886.3  1956.1   926.2  1967.7
#Mann= 3 , 0 , 0
       0      .1       0   436.2    .045       0   451.2      .1       0
Bank Sta=436.2,451.2
XS Rating Curve= 0 ,0
Exp/Cntr=0.3,0.1

Type RM Length L Ch R = 1 ,2934    ,93.3,92,90.6
XS GIS Cut Line= 2
     1821574.791      231972.052     1821691.688      232647.151
#Sta/Elev= 30
       0 1929.05    29.8 1912.32    49.6 1902.22    69.5 1895.86    89.4  1888.4
     139 1873.49   173.8 1861.54   193.6 1855.87   218.4 1849.66   263.1 1832.58
   273.1 1829.97   292.9 1826.98   332.6  1818.8     366 1813.42     381 1811.92
   387.3 1811.73   397.2  1812.2   407.1 1814.17   412.1 1814.48   431.9 1815.07
   466.7 1815.26   491.5 1817.42   501.4 1818.83   526.3 1825.32   556.1 1834.21
   580.9  1843.1   600.7 1851.09   620.6 1857.51   655.4 1867.58   685.1 1877.89
#Mann= 3 , 0 , 0
       0      .1       0     366    .045       0     381      .1       0
Bank Sta=366,381
XS Rating Curve= 0 ,0
Exp/Cntr=0.3,0.1

Type RM Length L Ch R = 1 ,2842    ,197.5,197.6,197.6
XS GIS Cut Line= 3
     1821443.607      231907.017     1821587.765      232521.557
     1821705.175      232783.612
#Sta/Elev= 30
       0 1969.77    19.9 1960.68    44.7 1947.32    59.6 1940.43    79.5 1932.52
   119.3 1918.79     169 1896.87   198.8 1885.11   273.4 1860.19   298.2 1849.85
   357.9 1829.95   437.4 1810.49   444.9 1810.08   459.9 1810.36   472.2 1809.87
     497 1812.35   561.6 1812.62   591.5 1815.33   601.4  1817.5   636.2 1828.26
   680.7 1844.69   705.5 1849.49   710.4  1851.2   725.3 1859.96   740.1  1866.3
   769.8 1875.43   799.6 1885.89     854 1902.38   903.5 1920.52   918.4 1925.05
#Mann= 3 , 0 , 0
       0      .1       0   444.9    .045       0   459.9      .1       0
Bank Sta=444.9,459.9
XS Rating Curve= 0 ,0
Exp/Cntr=0.3,0.1

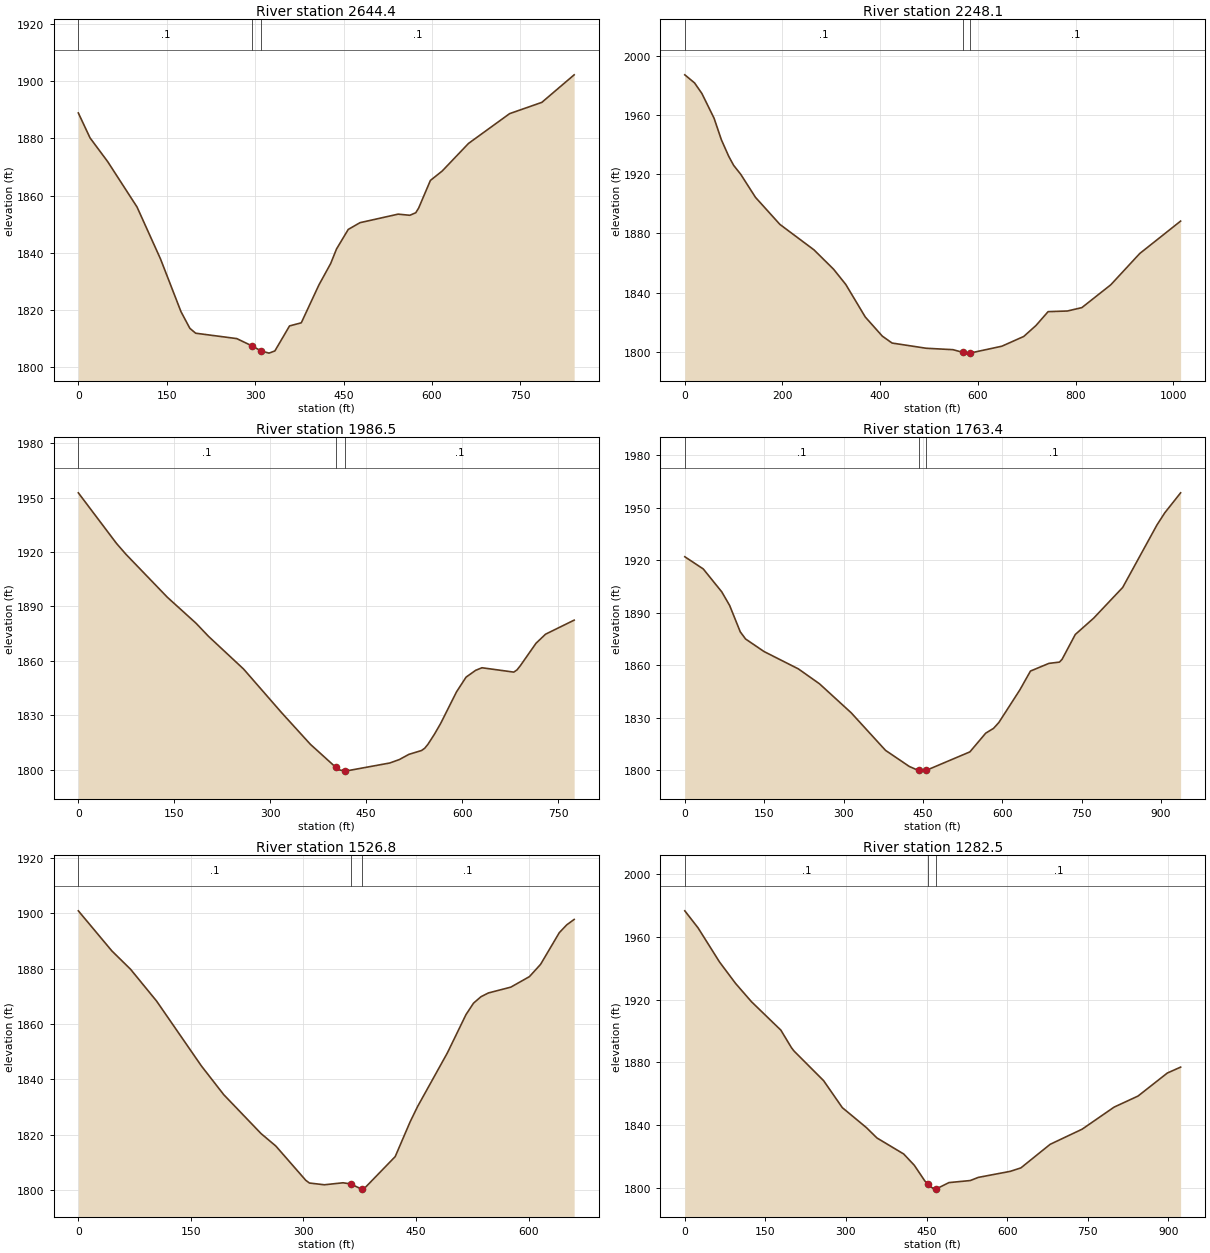
Type RM Length L Ch R = 1 ,2644.4  ,378.2,396.4,396.6
XS GIS Cut Line= 2
     1821292.378      232106.024     1821479.494      232926.217
#Sta/Elev= 30
       0 1888.94    19.9  1880.2    49.8  1871.9    99.6 1856.01   139.4 1837.84
   174.2 1819.36   189.2 1813.54   199.1 1811.82   268.8 1809.94   295.1 1807.34
   310.1 1805.62   323.6 1804.85   333.5 1805.62   358.4 1814.38   378.3 1815.46
   408.2 1828.72   428.1 1836.19   438.1 1841.32     458 1848.16   477.9 1850.52
   542.6 1853.51   562.5 1853.11   572.5    1854   577.4 1855.62   597.4 1865.32
   617.3 1868.59   662.1 1878.28   731.8  1888.7   786.5 1892.65   841.3 1902.29
#Mann= 3 , 0 , 0
       0      .1       0   295.1    .045       0   310.1      .1       0
Bank Sta=295.1,310.1
XS Rating Curve= 0 ,0
Exp/Cntr=0.3,0.1

Type RM Length L Ch R = 1 ,2248.1  ,258.6,261.5,264.5
XS GIS Cut Line= 3
     1821279.117      231897.369     1820971.162      232580.052
     1820790.366      232775.549
#Sta/Elev= 30
       0 1987.16      20 1981.69      35 1974.55    59.9 1957.86    74.9 1943.28
    89.9 1932.14    99.9 1926.06   114.8 1919.81   144.8 1904.34   194.7  1886.1
   264.6 1868.86   304.6 1855.82   329.5 1845.57   369.5 1823.53   404.4  1810.6
   424.4 1805.92   494.3  1802.4   549.2 1801.44   568.8 1799.66   579.2 1799.11
   583.8 1799.13   649.1 1803.77     694 1810.37     719 1817.76   743.9 1827.14
   783.4 1827.57     813 1829.86   872.2 1845.28   931.4 1866.39  1015.2 1888.33
#Mann= 3 , 0 , 0
       0      .1       0   568.8    .045       0   583.8      .1       0
Bank Sta=568.8,583.8
XS Rating Curve= 0 ,0
Exp/Cntr=0.3,0.1

Type RM Length L Ch R = 1 ,1986.5  ,221.8,223.1,223.6
XS GIS Cut Line= 2
      1821176.99      231875.247     1820762.215      232530.154
#Sta/Elev= 30
       0 1952.63    59.6 1924.77    74.5 1918.73   139.1 1895.08   183.9 1880.77
   203.7 1873.44   258.4 1855.46     318 1831.34   362.8 1813.98   402.4 1801.34
   407.5 1799.92   417.4 1799.19     487 1803.68   501.9 1805.57   516.8 1808.43
   536.7 1810.57   541.6 1811.82   546.6 1813.98   556.6 1819.45   566.5 1825.49
   591.3 1842.91   606.2 1851.01   621.2 1854.77   631.1 1856.18   680.8 1853.78
   685.8 1854.98   690.7 1857.15   715.6  1869.7   730.5 1874.69   775.2 1882.44
#Mann= 3 , 0 , 0
       0      .1       0   402.4    .045       0   417.4      .1       0
Bank Sta=402.4,417.4
XS Rating Curve= 0 ,0
Exp/Cntr=0.3,0.1

Type RM Length L Ch R = 1 ,1763.4  ,237.2,236.6,236.8
XS GIS Cut Line= 3
     1821048.091      231736.432     1820788.798      232103.233
     1820521.948      232511.681
#Sta/Elev= 30
       0 1921.89    34.9 1914.92    69.9 1901.81    84.8 1894.02   104.8    1879
   114.8  1874.9   149.7 1867.72   214.6  1857.8   254.5 1849.29   314.4 1832.72
   379.3 1811.24   424.2 1802.04   441.7 1799.71   449.2 1799.35   456.7 1799.84
   538.8 1810.35   568.7 1821.04   583.6 1823.81   593.6 1827.16   633.4 1845.86
   653.3 1856.55   688.2 1860.94   708.1 1861.67   713.1 1863.28     738 1877.45
   772.8  1886.8   827.6 1904.34   892.3 1940.03   907.2 1947.02   937.1 1958.43
#Mann= 3 , 0 , 0
       0      .1       0   441.7    .045       0   456.7      .1       0
Bank Sta=441.7,456.7
XS Rating Curve= 0 ,0
Exp/Cntr=0.3,0.1

Type RM Length L Ch R = 1 ,1526.8  ,239.4,244.3,245.7
XS GIS Cut Line= 2
     1820780.927       231713.08     1820412.932      232261.954
#Sta/Elev= 30
       0 1900.85    44.7 1886.37    69.6 1879.75   104.3 1868.26     164 1844.84
   193.8 1834.46   243.5 1820.42   263.3 1815.89   303.1 1803.54     308 1802.55
   327.9 1801.92   352.8 1802.64   362.8 1802.23   377.6 1800.35   377.8 1800.37
   382.6    1801   422.3 1812.09   442.2 1824.65   452.1 1830.16   491.9 1849.58
   516.7  1863.4   526.7 1867.51   536.6 1869.83   546.5 1871.19   576.4 1873.29
   601.2 1877.09   616.1 1881.54     641 1892.96   650.9 1895.78   660.8 1897.74
#Mann= 3 , 0 , 0
       0      .1       0   362.8    .045       0   377.8      .1       0
Bank Sta=362.8,377.8
XS Rating Curve= 0 ,0
Exp/Cntr=0.3,0.1

Type RM Length L Ch R = 1 ,1282.5  ,275.2,263.1,254.3
XS GIS Cut Line= 3
     1820763.344      231547.752     1820414.496      231835.464
     1820126.757      232208.278
#Sta/Elev= 30
       0 1976.52    24.8 1965.61    64.6 1943.95    94.4 1930.31   124.2 1918.58
   178.9 1900.48   198.8 1889.18   203.7 1887.06   258.4 1868.33   293.2 1851.14
   337.9 1838.46   357.8 1831.78   407.5  1821.6   427.3 1814.39   447.2 1804.26
   452.6 1802.35   462.1 1799.64   467.1  1799.2   467.6 1799.24   491.8 1803.36
   531.5 1804.67   546.4 1806.67   605.9 1810.53   625.7 1812.72   680.2 1827.75
   739.7 1837.38   799.2 1851.44   843.8  1858.5   898.3 1873.16   923.1 1876.94
#Mann= 3 , 0 , 0
       0      .1       0   452.6    .045       0   467.6      .1       0
Bank Sta=452.6,467.6
XS Rating Curve= 0 ,0
Exp/Cntr=0.3,0.1

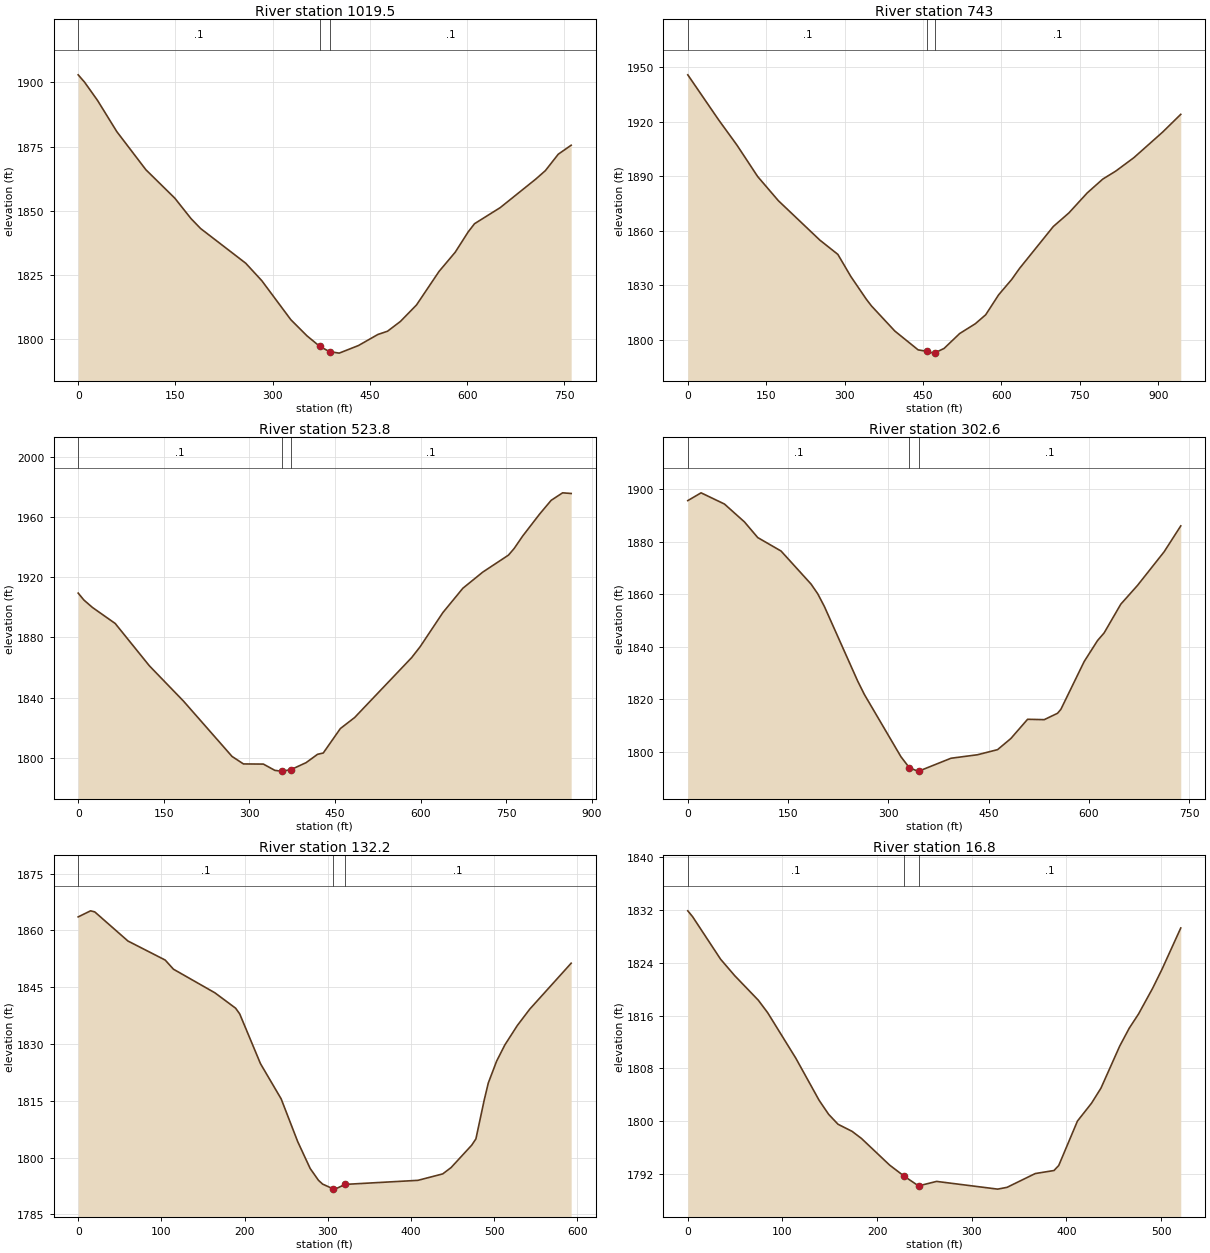
Type RM Length L Ch R = 1 ,1019.5  ,270.3,276.5,277.7
XS GIS Cut Line= 2
     1820275.713      231385.626     1820073.004      232118.498
#Sta/Elev= 30
       0 1902.93     9.9 1900.05    29.8 1892.98    59.6 1880.81   104.4 1865.98
   149.1 1854.89     174 1846.96   188.8 1843.09   258.4 1829.58   283.3 1822.75
     328 1807.58   352.9  1801.3   372.7 1797.18   372.7 1797.17   387.7 1795.15
   402.6 1794.57   432.4 1797.54   462.2 1801.83   477.1 1803.09     497  1806.9
   521.8 1813.31   556.6 1826.38   581.5 1833.84   601.4 1841.71   611.3 1844.95
     651 1851.23   705.7 1862.31   720.6 1865.62   740.5 1872.02   760.4 1875.52
#Mann= 3 , 0 , 0
       0      .1       0   372.7    .045       0   387.7      .1       0
Bank Sta=372.7,387.7
XS Rating Curve= 0 ,0
Exp/Cntr=0.3,0.1

Type RM Length L Ch R = 1 ,743     ,229.4,219.2,213.9
XS GIS Cut Line= 3
     1819978.685      231192.407     1819956.359      231657.411
     1819941.439       232134.93
#Sta/Elev= 30
       0 1945.94    59.4 1920.97    94.1 1907.21   133.7  1889.9   173.3 1876.59
   252.6 1854.89   287.2 1846.99     312 1834.81   341.7 1822.26   351.6 1818.55
   396.2 1804.75   440.8 1794.38     458 1793.56   470.5 1792.59     473 1792.77
   490.4 1795.17   520.3  1803.4   550.1 1808.77     570 1813.71   594.9 1824.76
   619.8 1833.18   634.7 1839.23   699.4 1862.35   729.3 1869.86   764.1 1880.81
     794 1888.47   818.9 1892.89   853.7 1900.32   908.5 1914.35   943.3 1924.17
#Mann= 3 , 0 , 0
       0      .1       0     458    .045       0     473      .1       0
Bank Sta=458,473
XS Rating Curve= 0 ,0
Exp/Cntr=0.3,0.1

Type RM Length L Ch R = 1 ,523.8   ,219.8,221.2,222.3
XS GIS Cut Line= 2
     1819807.922      231260.882     1819705.008      232118.498
#Sta/Elev= 30
       0 1909.47      10 1904.86      25 1899.92    64.9 1889.26   124.8 1861.11
   184.7  1837.6   269.6 1800.89   289.6 1795.91   324.5 1795.81   344.5 1791.66
   354.5 1791.13   357.4 1791.17   372.4 1792.06   399.4 1796.78   419.4 1802.31
   429.4 1803.17   459.4 1819.44   484.3 1826.72   584.2 1866.55   599.2 1873.84
   639.1 1896.56     674 1912.68     709 1923.45   753.9  1934.7   763.9 1939.12
   778.9 1947.42   808.8 1962.14   828.8 1971.15   848.8 1976.12   863.8 1975.68
#Mann= 3 , 0 , 0
       0      .1       0   357.4    .045       0   372.4      .1       0
Bank Sta=357.4,372.4
XS Rating Curve= 0 ,0
Exp/Cntr=0.3,0.1

Type RM Length L Ch R = 1 ,302.6   ,168,170.4,172.9
XS GIS Cut Line= 2
     1819627.256      231169.681     1819540.856      231901.918
#Sta/Elev= 30
       0 1895.72    19.9 1898.69    54.8 1894.42    84.7 1887.61   104.6 1881.63
   139.5 1876.49   184.3 1863.91   194.3 1860.21   204.3 1855.34   254.1  1826.9
     264 1821.83   318.8 1798.04   331.3 1793.87   343.8 1792.55   346.3 1792.63
   393.6 1797.46   433.4  1798.8   463.3 1800.74   483.2 1804.99   508.2 1812.32
   533.1 1812.18     553 1814.61     558 1816.12   592.8 1834.33   612.8 1842.34
   622.7 1845.27   647.6 1856.22   672.6 1863.38   712.4  1876.2   737.3 1886.08
#Mann= 3 , 0 , 0
       0      .1       0   331.3    .045       0   346.3      .1       0
Bank Sta=331.3,346.3
XS Rating Curve= 0 ,0
Exp/Cntr=0.3,0.1

Type RM Length L Ch R = 1 ,132.2   ,114.8,115.5,116.4
XS GIS Cut Line= 2
     1819482.981      231184.852     1819371.957      231766.968
#Sta/Elev= 30
       0 1863.56    14.9 1865.16    19.9 1864.88    59.8 1857.19   104.6 1852.16
   114.5 1849.75   164.3 1843.52   189.2 1839.46   194.2 1837.93   219.1 1824.82
     244  1815.5   263.9 1804.21   278.9 1797.12   288.8 1794.02   293.8 1793.01
   305.9 1791.81   308.8 1791.68   320.9 1792.93   408.4    1794   438.2  1795.7
   448.2 1797.36   473.1  1803.3   478.1 1804.95     488 1815.12     493 1819.71
     503 1825.48   512.9 1829.76   527.9 1834.89   542.8  1839.2   592.6 1851.33
#Mann= 3 , 0 , 0
       0      .1       0   305.9    .045       0   320.9      .1       0
Bank Sta=305.9,320.9
XS Rating Curve= 0 ,0
Exp/Cntr=0.3,0.1

Type RM Length L Ch R = 1 ,16.8    ,15.7,16.8,17.7
XS GIS Cut Line= 2
     1819375.993      231228.944     1819244.323      231732.722
#Sta/Elev= 30
       0 1831.88       5 1831.01    34.7 1824.54    49.6 1822.05    74.4 1818.35
    84.3 1816.46   114.1 1809.55   138.8 1803.15   148.8 1801.04   158.7 1799.54
   173.6 1798.46   183.5 1797.38   213.2 1793.35   228.7 1791.66   243.7  1790.2
   262.8 1790.88   327.3 1789.71   337.2 1789.98     367 1792.07   386.8 1792.53
   391.8 1793.29   411.6 1800.03   426.5 1802.74   436.4 1805.01   456.2 1811.38
   466.2 1814.08   476.1 1816.25     491 1820.15   500.9 1823.03   520.7 1829.28
#Mann= 3 , 0 , 0
       0      .1       0   228.7    .045       0   243.7      .1       0
Bank Sta=228.7,243.7
XS Rating Curve= 0 ,0
Exp/Cntr=0.3,0.1

Chan Stop Cuts=-1
Use User Specified Reach Order=0